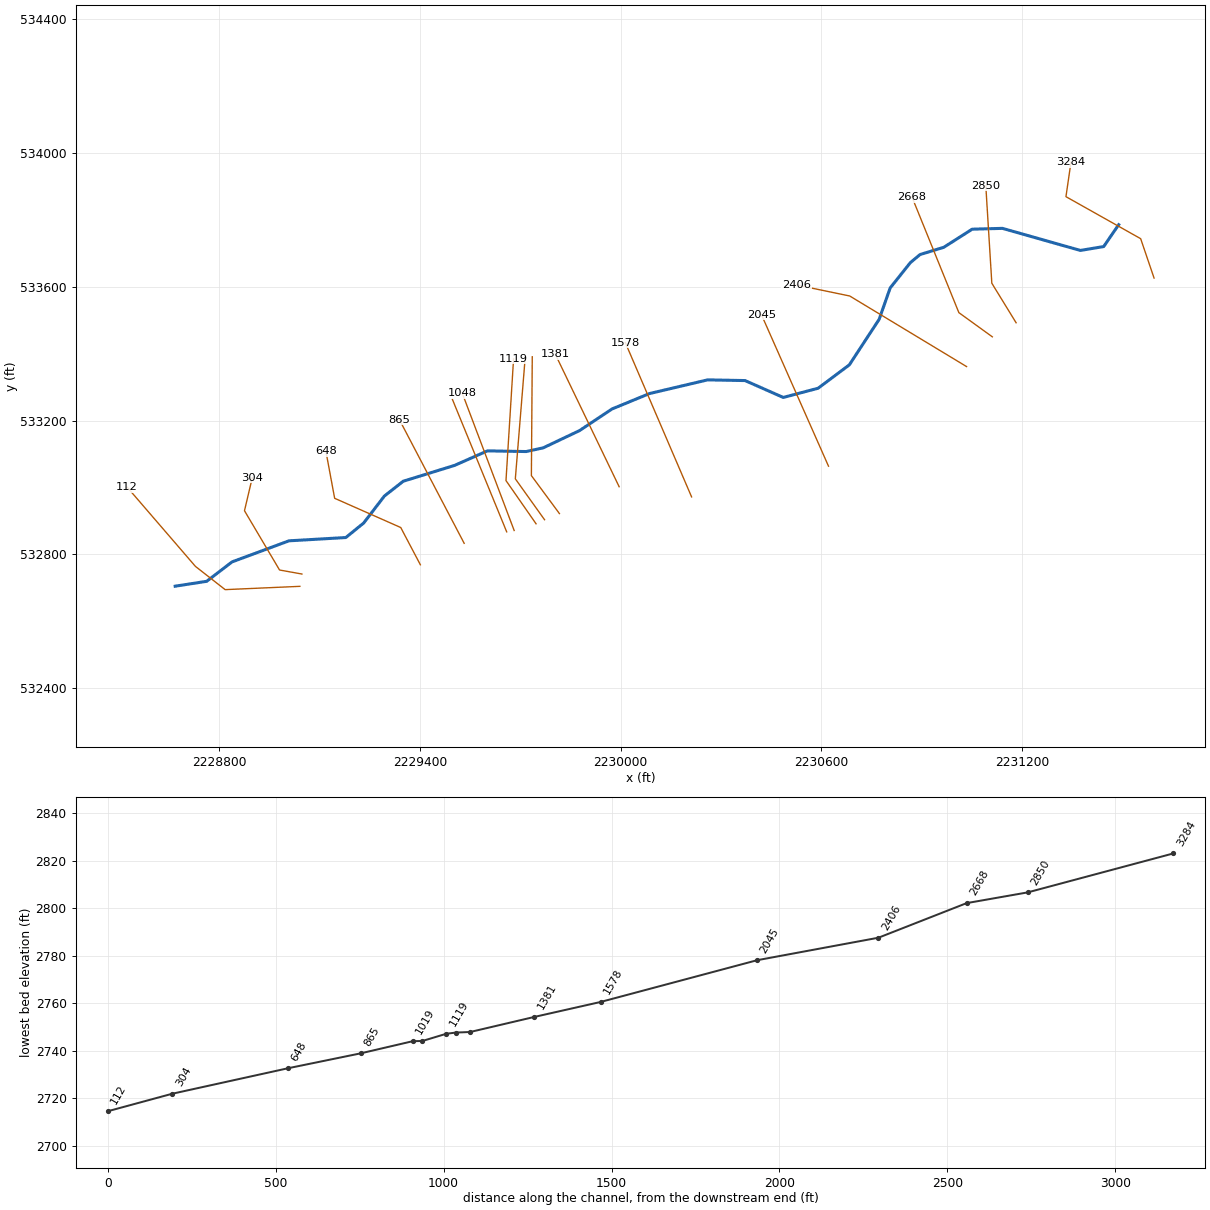
--- DOUGLASFK.prj (project) ---

Proj Title=DOUGLASFK
Current Plan=p01
Default Exp/Contr=0,0
English Units
Geom File=g01
Flow File=f01
Plan File=p01
BEGIN DESCRIPTION:
----------MODEL BY WOOD PLC 2021----------
Stream Name: Douglas Fork
Flood Zone: Approximate
Pocahontas County, WV
HEC-RAS Version: RAS 6.1
Vertical Datum: NAVD88
Projection: NAD 1983 StatePlane West Virginia S FIPS 4702 (US Feet)
Terrain: 1-meter LIDAR (FEMA Region III 3DEP collected 2016-2018)
Land Use: 2019 NLCD
Hydrologic Method:
WV SIR2010-5033 regression equations
END DESCRIPTION:
DSS Export Rating Curves= 0
DSS Export Rating Curve Sorted= 0
DSS Export Volume Flow Curves= 0
DXF OffsetX= 0
DXF OffsetY= 0
DXF ScaleX= 0
DXF ScaleY= 0

--- DOUGLASFK.p01 (plan) ---

Plan Title=Floodplain
Program Version=6.10
Short Identifier=Floodplain
Geom File=g01
Flow File=f01
Subcritical Flow
K Sum by GR= 0
Std Step Tol= 0.01
Critical Tol= 0.01
Num of Std Step Trials= 20
Max Error Tol= 0.3
Flow Tol Ratio= 0.001
Split Flow NTrial= 30
Split Flow Tol= 0.02
Split Flow Ratio= 0.02
Log Output Level= 0
Friction Slope Method= 1
Unsteady Friction Slope Method= 2
Unsteady Bridges Friction Slope Method= 1
Parabolic Critical Depth
Global Vel Dist= 0 , 0 , 0
Global Log Level= 0
CheckData=True
Encroach Param=-1 ,0,0, 0
Mapping Interval=1HOUR
Computation Time Step Use Courant=        0
Computation Time Step Use Time Series=    0
Computation Time Step Count To Double=0
Computation Time Step Max Doubling=0
Computation Time Step Max Halving=0
Computation Time Step Residence Courant=0
Run HTab= 0
Run UNet= 0
Run Sediment= 0
Run PostProcess= 0
Run WQNet= 0
Run RASMapper=-1
UNET Theta= 0
UNET Theta Warmup= 0
UNET ZTol= 0
UNET ZSATol= 0
UNET MxIter= 0
UNET Max Iter WO Improvement= 0
UNET MaxInSteps= 0
UNET DtIC= 0
UNET DtMin= 0
UNET MaxCRTS= 0
UNET WFStab= 0
UNET SFStab= 0
UNET WFX= 1
UNET SFX= 1
UNET Gravity=32.174
UNET 1D Methodology=Finite Difference
UNET DSS MLevel= 1
UNET Pardiso=0
UNET DZMax Abort= 0
UNET Use Existing IB Tables= 0
UNET Froude Reduction=False
UNET Froude Limit= 0
UNET Froude Power= 0
UNET D1 Cores= 0
UNET WindReference=Eulerian
UNET WindDragFormulation=Hsu (1988)
UNET D2 Coriolis=0
UNET D2 Cores= 0
UNET D2 Theta= 1
UNET D2 Theta Warmup= 1
UNET D2 Z Tol= 0.01
UNET D2 Volume Tol= 0.01
UNET D2 Max Iterations= 20
UNET D2 Equation= 0
UNET D2 RampUpFraction=0.1
UNET D2 TimeSlices= 1
UNET D2 Turbulence Formulation=Non-Conservative (original)
UNET D2 Eddy Viscosity=0.3
UNET D2 Transverse Eddy Viscosity=0.1
UNET D2 Smagorinsky Mixing=0
UNET D2 BCVolumeCheck=0
UNET D2 Cores=0
UNET D2 SolverType=PARDISO (Direct)
UNET D2 Minimum Iterations= 2147483647
UNET D2 Maximum Iterations= 2147483647
UNET D2 Restart Number= 10
UNET D2 Relaxation Coeff=1.3
UNET D2 SOR Precondition Iterations= 10
UNET D2 ILUT Maximum Fill= 8
UNET D2 ILUT Tolerance=1E-08
UNET D1D2 MaxIter= 0
UNET D1D2 ZTol=0.01
UNET D1D2 QTol=0.1
UNET D1D2 MinQTol=1
Write IC File= 0
Write IC File at Fixed DateTime=0
Write IC File at Sim End=0
Echo Input=False
Echo Parameters=False
Echo Output=False
Write Detailed= 0
HDF Write Warmup=0
HDF Write Time Slices=0
HDF Flush=0
HDF Compression= 1
HDF Chunk Size= 1
HDF Spatial Parts= 1
HDF Use Max Rows=0
HDF Fixed Rows= 1
Calibration Method= 0
Calibration Iterations= 20
Calibration Max Change=0.05
Calibration Tolerance=0.2
Calibration Maximum=1.5
Calibration Minimum=0.5
Calibration Optimization Method= 1
WQ AD Non Conservative
WQ ULTIMATE=-1
WQ Max Comp Step=1HOUR
WQ Output Interval=15MIN
WQ Output Selected Increments= 0
WQ Output face flow=0
WQ Output face velocity=0
WQ Output face area=0
WQ Output face dispersion=0
WQ Output cell volume=0
WQ Output cell surface area=0
WQ Output cell continuity=0
WQ Output cumulative cell continuity=0
WQ Output face conc=0
WQ Output face dconc_dx=0
WQ Output face courant=0
WQ Output face peclet=0
WQ Output face adv mass=0
WQ Output face disp mass=0
WQ Output cell mass=0
WQ Output cell source sink temp=0
WQ Output nsm pathways=0
WQ Output nsm derived pathways=0
WQ Create Restart=0
WQ Fixed Restart=0
WQ System Summary=0
WQ Write To DSS=0
Sorting and Armoring Iterations= 10
XS Update Threshold= 0.02
Bed Roughness Predictor= 0
Hydraulics Update Threshold= 0.02
Energy Slope Method= 1
Volume Change Method= 1
Sediment Retention Method= 0
Sediment TS Multiplier= 1
Warm Up Method= 0
XS Weighting Method= 0
Number of US Weighted Cross Sections= 1
Number of DS Weighted Cross Sections= 1
Upstream XS Weight=0
Main XS Weight=1
Downstream XS Weight=0
Number of DS XS's Weighted with US Boundary= 1
Upstream Boundary Weight= 1
Weight of XSs Associated with US Boundary= 0
Number of US XS's Weighted with DS Boundary= 1
Downstream Boundary Weight= 0.5
Weight of XSs Associated with DS Boundary= 0.5
Percentile Method= 0
Sediment Output Level= 3
Mass or Volume Output= 0
Output Increment Type= 1
Profile and TS Output Increment= 1
Transport Output Increment 1
XS Output Flag= 0
XS Output Increment= 10
Read HDF5 Sediment Hotstart= 0
Sediment Hotstart Type= 0
Write Gradation File= 0
Read Gradation Hotstart= 0
Write HDF5 File= 1
Write Binary Output= 1
Write DSS Sediment File= 0
DSS Sediment Output Type= 1
SV Curve= 0
Specific Gage Flag= 0
Subcell Erosion Methods= 0
Subcell Deposition Methods= 0
Advection Scheme= 1
Matrix Solver= 0
Implicit Weighting Factor= 1
Maximum Outer Loop Convergence Iterations= 5
Convergence Maximum Absolute= 0.001
Convergence RMSE= 0.0001
Grain Fractions Max Abs Error= 0.001
Max Subgrid Regions= 1
Max Subgrid Length Scale= 3.402823E+38
Initial Layer Thickness= 3.402823E+38
Min Layer Thickness= 3.402823E+38
Max Layer Thickness= 3.402823E+38
Number of Layers= 5

--- DOUGLASFK.f01 (steady flow) ---

Flow Title=Flow
Program Version=6.10
Number of Profiles= 6
Profile Names=01pct,10pct,04pct,02pct,0_2pct,01plus
River Rch & RM=DOUGLASFK,Main            ,3284
     602     319     423     510     840     890
Boundary for River Rch & Prof#=DOUGLASFK,Main            , 1
Up Type= 0
Dn Type= 3
Dn Slope=0.02576
Boundary for River Rch & Prof#=DOUGLASFK,Main            , 2
Up Type= 0
Dn Type= 3
Dn Slope=0.02576
Boundary for River Rch & Prof#=DOUGLASFK,Main            , 3
Up Type= 0
Dn Type= 3
Dn Slope=0.02576
Boundary for River Rch & Prof#=DOUGLASFK,Main            , 4
Up Type= 0
Dn Type= 3
Dn Slope=0.02576
Boundary for River Rch & Prof#=DOUGLASFK,Main            , 5
Up Type= 0
Dn Type= 3
Dn Slope=0.02576
Boundary for River Rch & Prof#=DOUGLASFK,Main            , 6
Up Type= 0
Dn Type= 3
Dn Slope=0.02576
DSS Import GetInterval= 0
DSS Import GetPeak= 0
DSS Import FillOption= 0

--- DOUGLASFK.g01 (geometry) ---

Geom Title=Geometry
Program Version=6.10

River Reach=DOUGLASFK       ,Main
Reach XY= 30
2231488.66900003533785.4370000062231443.92900005533720.201000005
     2231374.265 533708.490000012231141.35200003533774.474999994
     2231050.936533772.0440000152230966.15299998533717.979000002
     2230895.192 533696.282000022230865.92900005533671.833000019
     2230805.764 533596.331000032230772.78300002533502.569000006
2230683.72300002533366.5300000012230590.43200001533296.688999996
2230486.29600002533269.1379999972230372.18700001533319.606999993
2230260.25100002533321.7130000142230086.42500001533280.759000018
     2229974.383533234.6260000022229877.39300001533170.068000004
2229768.93900001533118.5780000092229717.84200004533107.476000026
     2229602.439533109.569000006     2229504.142533066.123000011
2229350.67900002533018.8130000082229294.21600004532974.498999998
2229232.36575559  532893.93425082229179.02500002532850.497000009
2229009.11399998532840.6910000152228839.02099998532777.748999998
2228763.14900002532719.6509999932228669.00287446 532705.07015048

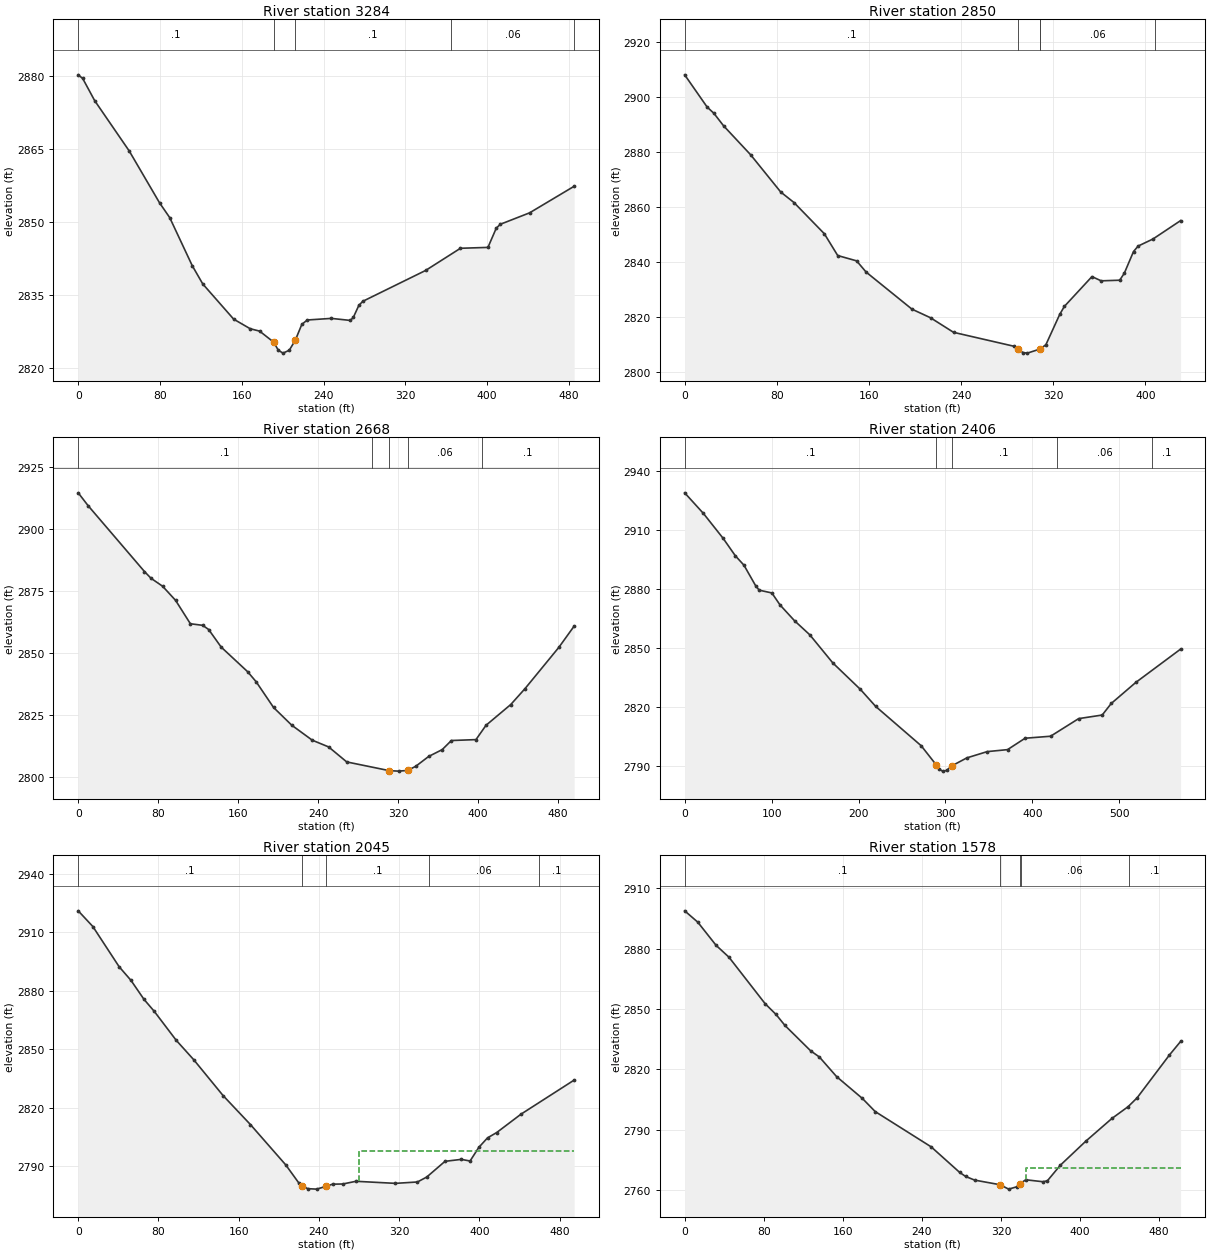
Type RM Length L Ch R = 1 ,3284    ,446.5,433.8,416.1
XS GIS Cut Line= 4
2231594.42788649533625.9042899312231554.36364874  533743.6403774
2231331.09038651 533869.208122792231346.14579122  533972.5742416
#Sta/Elev= 30
       0 2880.19     4.4 2879.44    16.1  2874.9    49.9 2864.58    79.5 2853.97
    89.5 2850.92   111.5 2841.08   121.8 2837.33     152 2830.12   168.2 2828.15
   177.4 2827.66   191.1 2825.41   195.7 2823.74   200.3 2823.15   206.4 2823.74
   212.3 2825.79   218.7 2829.05     224 2829.94   247.5 2830.27   266.2 2829.85
   269.1 2830.49   274.4 2832.92   278.3 2833.77   339.7 2840.09   373.8 2844.64
   400.7 2844.82   408.8 2848.75   412.8 2849.56   441.4  2851.9     485 2857.35
#Mann= 5 ,-1,0
       0      .1       0   191.1    .045       0   212.3      .1       0
  364.37     .06       0  484.98      .1       0
Bank Sta=191.1,212.3
XS Rating Curve= 0 ,0
Exp/Cntr=0.3,0.1

Type RM Length L Ch R = 1 ,2850    ,174.7,182,184.3
XS GIS Cut Line= 3
2231182.10068407533492.3403194482231109.57739152533610.498719639
2231091.54794898533902.023924664
#Sta/Elev= 30
       0 2908.17    19.5 2896.42    25.3 2894.18    33.8 2889.58    57.3 2879.02
    83.4 2865.46    94.9 2861.63   121.3 2850.24   132.9  2842.3   149.3 2840.36
   157.6 2836.26   197.4 2822.75   213.5 2819.62   233.5 2814.31   285.6 2809.27
   289.7 2808.41   293.6 2806.94   297.6 2806.73   308.6 2808.22   313.7  2809.8
   325.7 2820.83   329.7 2823.74   353.7 2834.62   361.7 2833.08   377.8 2833.31
   381.8 2835.86   389.8 2843.76   393.8 2845.75   406.7 2848.33   430.7 2855.04
#Mann= 5 ,-1,0
       0      .1       0   289.7    .045       0   308.6      .1       0
  308.64     .06       0  408.64      .1       0
Bank Sta=289.7,308.6
XS Rating Curve= 0 ,0
Exp/Cntr=0.3,0.1

Type RM Length L Ch R = 1 ,2668    ,251.8,262.7,269.8
XS GIS Cut Line= 3
2231111.10612762533450.3127033912231011.05448454533522.647337234
2230871.04227532533867.945687984
#Sta/Elev= 30
       0 2914.42     9.9 2909.24    66.3 2882.67    72.9 2879.94    84.4 2876.76
    97.4 2871.06   112.2 2861.63   124.5 2860.99   130.5  2859.3     143 2852.22
   169.4 2842.32     178 2838.24   195.4 2827.87   213.6 2820.72   234.1 2814.68
   250.5 2811.96   268.6 2805.91   311.2 2802.39   320.4  2802.2   329.42802.472
   337.7 2804.16   350.6 2808.13   364.1 2810.87   373.3 2814.54   397.9 2814.91
   407.9 2820.67   432.7 2829.06     447 2835.49   480.8 2852.11   496.1 2860.68
#Mann= 5 ,-1,0
       0      .1       0  293.46     .06       0   311.2    .045       0
   329.4     .06       0  403.46      .1       0
Bank Sta=311.2,329.4
XS Rating Curve= 0 ,0
Exp/Cntr(USF)=0,0
Exp/Cntr=0.3,0.1

Type RM Length L Ch R = 1 ,2406    ,369.1,361.2,350.1
XS GIS Cut Line= 3
2231034.06244329533361.4557835372230684.88959115533572.357967526
2230525.71267012533605.379822944
#Sta/Elev= 30
       0 2928.97    21.6 2918.48    44.3 2905.82    58.3 2896.98    68.2 2892.21
    81.6 2881.81    85.7 2879.54   100.3 2878.11   109.7 2872.02   126.4 2863.99
   143.9 2856.87   170.4 2842.58   202.2 2829.11   219.7  2820.5   272.1  2800.5
   289.6 2790.67   292.5 2788.73   296.6 2787.62   301.3 2787.94   307.1 2790.25
   324.6 2794.35     348 2797.53   371.4 2798.54   391.6 2804.33   420.9 2805.34
   453.2 2814.29   480.3 2816.11   490.7 2821.98     519 2832.69   570.5  2849.6
#Mann= 5 ,-1,0
       0      .1       0   289.6    .045       0   307.1      .1       0
  427.92     .06       0  537.92      .1       0
Bank Sta=289.6,307.1
XS Rating Curve= 0 ,0
Exp/Cntr=0.3,0.1

Type RM Length L Ch R = 1 ,2045    ,462.7,466.2,460.8
XS GIS Cut Line= 2
2230621.44892901 533063.862441292230421.26048358533516.091770126
#Sta/Elev= 30
       0    2921    14.6 2912.94    40.8 2892.31    52.6 2885.32    65.6 2875.56
    75.8 2869.43    97.7 2854.57   115.2 2844.57   144.5 2826.15   171.8 2811.26
     207 2790.57   220.3  2781.1   223.3 2779.88   228.9 2778.38   237.7 2778.14
  247.572779.605   253.6 2780.68   263.9 2780.78     277 2782.16   316.4  2781.1
   338.3 2781.81   347.6 2784.35   365.8 2792.41     382 2793.41   390.8 2792.58
   399.5 2799.56   408.2 2804.45   417.4  2807.2   441.6 2816.62   494.6 2834.12
#Mann= 5 ,-1,0
       0      .1       0   223.3    .045       0  247.57      .1       0
     350     .06       0     460      .1       0
#XS Ineff= 2 , 0
                          279.88         2797.49
Permanent Ineff=
       F       F
Bank Sta=223.3,247.57
XS Rating Curve= 0 ,0
Exp/Cntr(USF)=0,0
Exp/Cntr=0.3,0.1

Type RM Length L Ch R = 1 ,1578    ,196.4,197.4,197.8
XS GIS Cut Line= 2
 2230212.2942488532971.9817712342230014.28830175533433.010543463
#Sta/Elev= 30
       0 2898.79    13.2 2893.19    31.8 2881.64    44.8 2875.76    81.4 2852.66
    92.4 2847.33   101.5 2841.83   127.5 2829.23   136.3 2826.18   153.7 2816.44
   179.8 2805.59   192.8 2799.06   249.4 2781.54   278.1 2768.91   284.2 2766.85
   293.4 2765.02   319.1 2762.73   327.8 2760.54     336  2761.7     339 2763.23
   345.2 2765.18   362.6 2764.21     367 2764.68     380 2772.37     406 2784.42
   432.3 2795.65   448.7 2801.51   457.8 2805.91   490.4 2827.12   501.8  2833.9
#Mann= 5 ,-1,0
       0      .1       0   319.1    .045       0     339      .1       0
     340     .06       0     450      .1       0
#XS Ineff= 1 ,-1
  345.62501.7508 2771.28
Permanent Ineff=
       F
Bank Sta=319.1,339
XS Rating Curve= 0 ,0
Exp/Cntr(USF)=0,0
Exp/Cntr=0.3,0.1

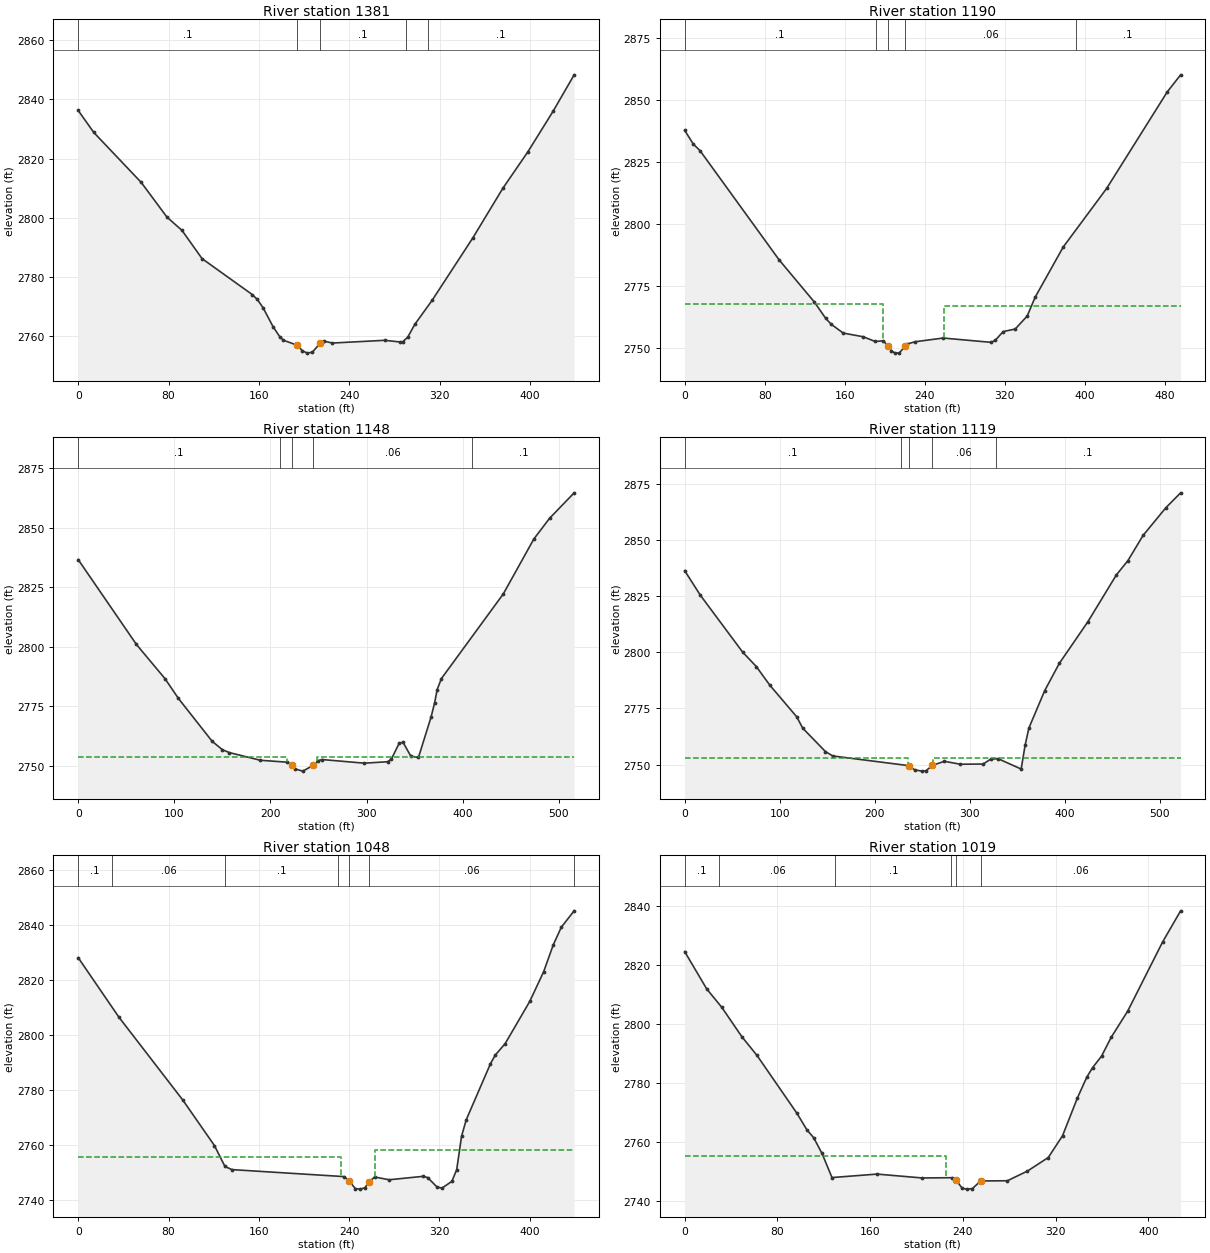
Type RM Length L Ch R = 1 ,1381    ,197.7,190.8,185.7
XS GIS Cut Line= 2
 2229995.8182207533002.3526333952229805.20009261533398.014045211
#Sta/Elev= 30
       0 2836.23    13.8  2828.8    55.8 2811.92    78.6 2800.19    91.9 2795.71
   109.7 2786.16   154.1 2774.03   158.5 2772.42   163.7 2769.57   172.6 2763.14
   178.6 2759.71   181.6  2758.6   194.1 2756.88   198.5 2755.04   202.9 2754.23
   207.4 2754.57   214.3  2757.6   217.6 2758.28   225.1 2757.64   271.5 2758.56
   284.9    2758   287.3 2758.07   291.7 2759.54   298.1 2763.96   313.5 2772.12
   349.5 2793.19   376.1 2809.97   398.3 2822.31   420.5 2835.94   439.2 2848.28
#Mann= 5 ,-1,0
       0      .1       0   194.1    .045       0   214.3      .1       0
     290     .06       0     310      .1       0
Bank Sta=194.1,214.3
XS Rating Curve= 0 ,0
Exp/Cntr(USF)=0,0
Exp/Cntr=0.3,0.1

Type RM Length L Ch R = 1 ,1190    ,43,42.1,41
XS GIS Cut Line= 3
2229817.30902412532922.1509701542229733.54506113533035.581336701
2229736.16268497533390.705638123
#Sta/Elev= 30
       0 2837.82     8.6 2832.29    15.4  2829.6    94.5 2785.52   129.8 2768.48
     141 2761.97   146.6 2759.53   158.6 2755.98   178.6  2754.5   190.6 2752.59
   198.6 2752.87  203.832750.679   206.6 2748.83   210.6 2747.89   214.6 2747.95
   220.6 2750.64   220.6 2750.67   222.6 2751.58   230.6 2752.49   258.6 2753.98
   306.6 2752.24   310.6 2753.03   318.6 2756.59   330.6 2757.61   342.6 2762.85
   350.6 2770.47   378.6 2790.68   422.1 2814.37   482.7 2853.32   496.1 2860.23
#Mann= 5 ,-1,0
       0      .1       0  191.01     .06       0  203.83    .045       0
   220.6     .06       0  391.01      .1       0
#XS Ineff= 2 , 0
          198.62 2767.55  259.55         2766.84
Permanent Ineff=
       F       F
Bank Sta=203.83,220.6
XS Rating Curve= 0 ,0
Exp/Cntr(USF)=0,0
Exp/Cntr=0.5,0.3

Type RM Length L Ch R = 1 ,1148    ,28.8,29.1,29.5
XS GIS Cut Line= 3
2229772.80941878 532903.827603252229685.55529067533025.983382609
2229715.22169422533390.705638123
#Sta/Elev= 30
       0 2836.52    60.6 2800.87    90.3 2786.51   104.3 2778.18   139.3 2760.22
   150.1 2756.63   157.3 2755.45   189.4 2752.23   217.5 2751.41   222.3 2750.28
   225.6 2748.58   233.6 2747.66   244.6 2750.09   249.6 2752.03   253.7 2752.53
   297.8    2751   321.9 2751.61   325.9 2752.77   333.9 2759.34   337.9 2759.82
     346 2753.99     354 2753.39   367.1 2770.35   370.8 2776.29   373.5 2781.94
   377.9 2786.56   442.3 2822.13     474 2845.15   490.4 2853.88     516 2864.59
#Mann= 5 ,-1,0
       0      .1       0  210.12     .06       0   222.3    .045       0
   244.6     .06       0  410.12      .1       0
#XS Ineff= 2 , 0
          217.68 2753.53  248.87         2753.65
Permanent Ineff=
       F       F
Bank Sta=222.3,244.6
XS Rating Curve= 0 ,0
Exp/Cntr(USF)=0,0
Exp/Cntr=0.5,0.3

Type RM Length L Ch R = 1 ,1119    ,64.1,70.8,76.9
XS GIS Cut Line= 3
2229747.50572163532891.6120253142229657.63396967533020.748134922
2229680.32004298533384.597849155
#Sta/Elev= 30
       0 2836.31    16.5 2825.38      61 2800.09    75.4 2793.64    89.6 2785.37
   117.9 2771.31   124.2 2766.26   148.1 2755.85   155.8 2753.89   236.3 2749.55
   241.9  2747.7   249.9 2747.14   253.9 2747.28  260.642749.677   273.3 2751.52
     290 2750.21   314.1 2750.29   322.1 2752.49   329.9 2752.66   354.1 2748.07
   358.2 2758.54   362.2 2766.28   378.9 2782.97   394.2 2795.04   424.4 2813.65
   454.3 2834.42   466.4 2840.75   482.4 2851.99   506.4 2864.32   521.9 2870.93
#Mann= 5 ,-1,0
       0      .1       0  227.33     .06       0   236.3    .045       0
  260.64     .06       0  327.33      .1       0
#XS Ineff= 2 ,-1
       0  235.46    2753  261.41521.8873    2753
Permanent Ineff=
       F       F
Bank Sta=236.3,260.64
XS Rating Curve= 0 ,0
Exp/Cntr(USF)=0,0
Exp/Cntr=0.5,0.3

Type RM Length L Ch R = 1 ,1048    ,28.7,29.1,29.4
XS GIS Cut Line= 2
2229682.06512554532871.543575848 2229526.7527775533282.510519262
#Sta/Elev= 30
       0 2828.18      36  2806.6    92.7 2776.44   120.7 2759.93     130 2752.33
   136.2  2751.2   235.5 2748.66   240.1 2747.03   245.5 2744.31   249.8 2744.11
   254.1 2744.62   257.2 2746.61   262.6 2748.52   275.4 2747.51   305.4 2748.75
   309.6 2748.31   318.2 2744.74   322.4 2744.54     331 2746.92   335.3 2751.19
   339.6 2763.34   343.8 2769.37   365.2 2789.65   369.5 2792.82   378.2 2796.96
     400 2812.29   412.3 2823.06   420.8 2832.79   427.9  2839.2   439.3  2845.2
#Mann= 7 ,-1,0
       0      .1       0      30     .06       0     130      .1       0
     230     .06       0   240.1    .045       0   257.2     .06       0
  439.34      .1       0
#XS Ineff= 2 , 0
          233.18 2755.75  262.82         2758.45
Permanent Ineff=
       F       F
Bank Sta=240.1,257.2
XS Rating Curve= 0 ,0
Exp/Cntr(USF)=0,0
Exp/Cntr=0.5,0.3

Type RM Length L Ch R = 1 ,1019    ,152.8,154.4,155.6
XS GIS Cut Line= 2
2229659.74074883532867.5591446382229497.45774789533263.529666931
#Sta/Elev= 30
       0 2824.43      19  2811.8      32 2805.57    49.3 2795.63    62.3 2789.33
    96.9 2769.66   105.5 2764.05   111.3 2761.42   118.5 2756.08   127.1 2747.93
     166  2749.1   204.9 2747.79   230.9 2747.88   233.9 2747.21   239.5 2744.27
   243.8 2744.01   248.2 2744.19   255.4 2746.78   278.4 2746.84   295.7 2750.11
   313.7 2754.71     326 2762.07   338.9 2774.93   346.9 2781.88   351.9 2785.12
   359.7 2789.05     368 2795.41   382.2 2804.25   412.4 2827.72   427.9 2838.23
#Mann= 6 ,-1,0
       0      .1       0      30     .06       0     130      .1       0
     230     .06       0   233.9    .045       0   255.4     .06       0
#XS Ineff= 2 , 0
          225.58 2755.06
Permanent Ineff=
       F       F
Bank Sta=233.9,255.4
XS Rating Curve= 0 ,0
Exp/Cntr(USF)=0,0
Exp/Cntr=0.5,0.3

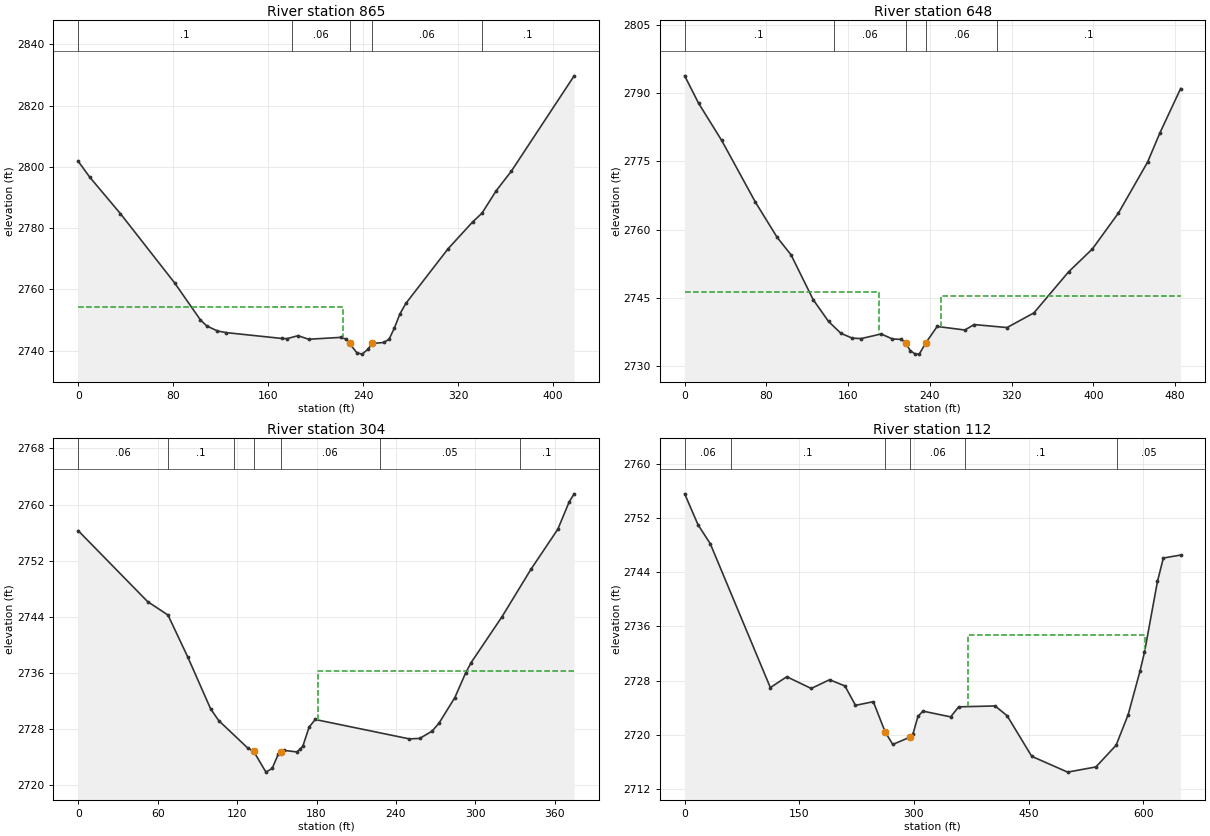
Type RM Length L Ch R = 1 ,865     ,205.9,216.6,225.5
XS GIS Cut Line= 2
2229532.69634238532833.2478815822229338.88407268533203.253123725
#Sta/Elev= 30
       0 2801.81     9.7 2796.64    35.6 2784.71    81.2 2762.14   102.9 2750.09
   108.3  2748.1   117.3 2746.46   124.8 2745.92   171.5 2744.02     176 2743.96
   185.1 2744.93   194.1 2743.76   221.2 2744.38   225.7 2743.79   228.5 2742.41
   234.7 2739.34   239.2 2738.91   243.8 2740.44   247.72742.392   257.3 2742.71
   261.8 2743.76   266.3 2747.43   270.9 2751.99   275.9 2755.43   311.5 2773.27
   332.2 2782.03     340 2784.85   352.1 2792.23   364.8 2798.59   417.7 2829.68
#Mann= 5 ,-1,0
       0      .1       0     180     .06       0   228.5    .045       0
   247.7     .06       0     340      .1       0
#XS Ineff= 2 , 0
          223.06 2754.34
Permanent Ineff=
       F       F
Bank Sta=228.5,247.7
XS Rating Curve= 0 ,0
Exp/Cntr(USF)=0,0
Exp/Cntr=0.3,0.1

Type RM Length L Ch R = 1 ,648     ,353.2,344.7,337.3
XS GIS Cut Line= 4
 2229401.7759552532769.1143671792229343.12777581532880.426217859
2229145.63900848532967.8000361352229119.30717283 533109.03442732
#Sta/Elev= 30
       0 2793.78    13.6 2787.76    36.2 2779.59    69.3 2765.99    90.5 2758.29
   104.1 2754.44   125.8 2744.58   140.8  2739.8   152.9  2737.2     164 2736.13
   172.8 2736.04   192.3 2737.05   203.4 2735.95   212.2 2735.86   216.4    2735
   220.9 2733.37   225.7 2732.62   229.6 2732.64  235.922735.058   247.1  2738.7
   274.2 2737.92   283.3 2739.12   315.5 2738.46   341.8 2741.68   375.7 2750.69
   399.1 2755.75   424.6 2763.65     453 2774.79   465.2 2781.27   485.4 2790.98
#Mann= 5 ,-1,0
       0      .1       0  145.82     .06       0   216.4    .045       0
  235.92     .06       0  305.82      .1       0
#XS Ineff= 2 , 0
          190.24  2746.2  250.72         2745.36
Permanent Ineff=
       F       F
Bank Sta=216.4,235.92
XS Rating Curve= 0 ,0
Exp/Cntr(USF)=0,0
Exp/Cntr=0.3,0.1

Type RM Length L Ch R = 1 ,304     ,192.2,192.2,192.2
XS GIS Cut Line= 4
2229047.70200242532741.4420696212228980.93413918532753.497378263
2228876.14568715532930.6176821462228899.32897299533028.914814144
#Sta/Elev= 30
       0 2756.28    52.4 2746.18    67.8 2744.26    82.8 2738.26     100  2730.9
   106.1 2729.23   127.9 2725.34   132.4 2724.88   141.8 2721.88   146.5 2722.41
   151.1 2724.44   152.9 2724.72   155.8 2724.97   165.1 2724.76   167.5 2725.13
   169.7  2725.6   174.4 2728.29     179 2729.38     250 2726.62   257.9 2726.68
   267.3 2727.72   272.6 2728.88   284.5 2732.51   292.7 2736.04   296.8 2737.49
   320.1 2744.02     342 2750.79   362.3  2756.5   370.8 2760.37   374.6 2761.53
#Mann= 7 ,-1,0
       0     .06       0   67.85      .1       0  117.85     .06       0
   132.4    .045       0   152.9     .06       0  227.85     .05       0
  333.64      .1       0
#XS Ineff= 2 , 0
                          181.26         2736.24
Permanent Ineff=
       F       F
Bank Sta=132.4,152.9
XS Rating Curve= 0 ,0
Exp/Cntr(USF)=0,0
Exp/Cntr=0.3,0.1

Type RM Length L Ch R = 1 ,112     ,,,
XS GIS Cut Line= 4
 2229041.6271884532704.6649574352228818.37805422532694.820174287
2228729.53407181532764.3080720962228525.46402952 533001.10571862
#Sta/Elev= 30
       0 2755.55    17.5 2750.98    33.5 2748.19   112.1 2726.97   133.6 2728.57
   165.6 2726.84   189.6 2728.13   209.7 2727.21   223.5 2724.35   246.8 2724.89
262.25922720.441   272.3 2718.58   295.1 2719.68   298.7 2720.13   305.2 2722.71
   311.7  2723.5     348 2722.65   358.5 2724.13   406.1 2724.26   421.9 2722.82
   454.1 2716.83   501.1  2714.5   538.1 2715.27   564.5 2718.47   580.3 2722.99
   595.7 2729.38   601.6 2732.17   618.6 2742.63   626.3 2746.08   648.9 2746.52
#Mann= 6 ,-1,0
       0     .06       0      60      .1       0262.2592    .045       0
   295.1     .06       0  366.26      .1       0  566.26     .05       0
#XS Ineff= 1 ,-1
  370.51  602.07 2734.77
Permanent Ineff=
       F
Bank Sta=262.2592,295.1
XS Rating Curve= 0 ,0
Exp/Cntr(USF)=0,0
Exp/Cntr=0.3,0.1
LCMann Table=0

Chan Stop Cuts=-1
Use User Specified Reach Order=0
Composite Channel Slope=5